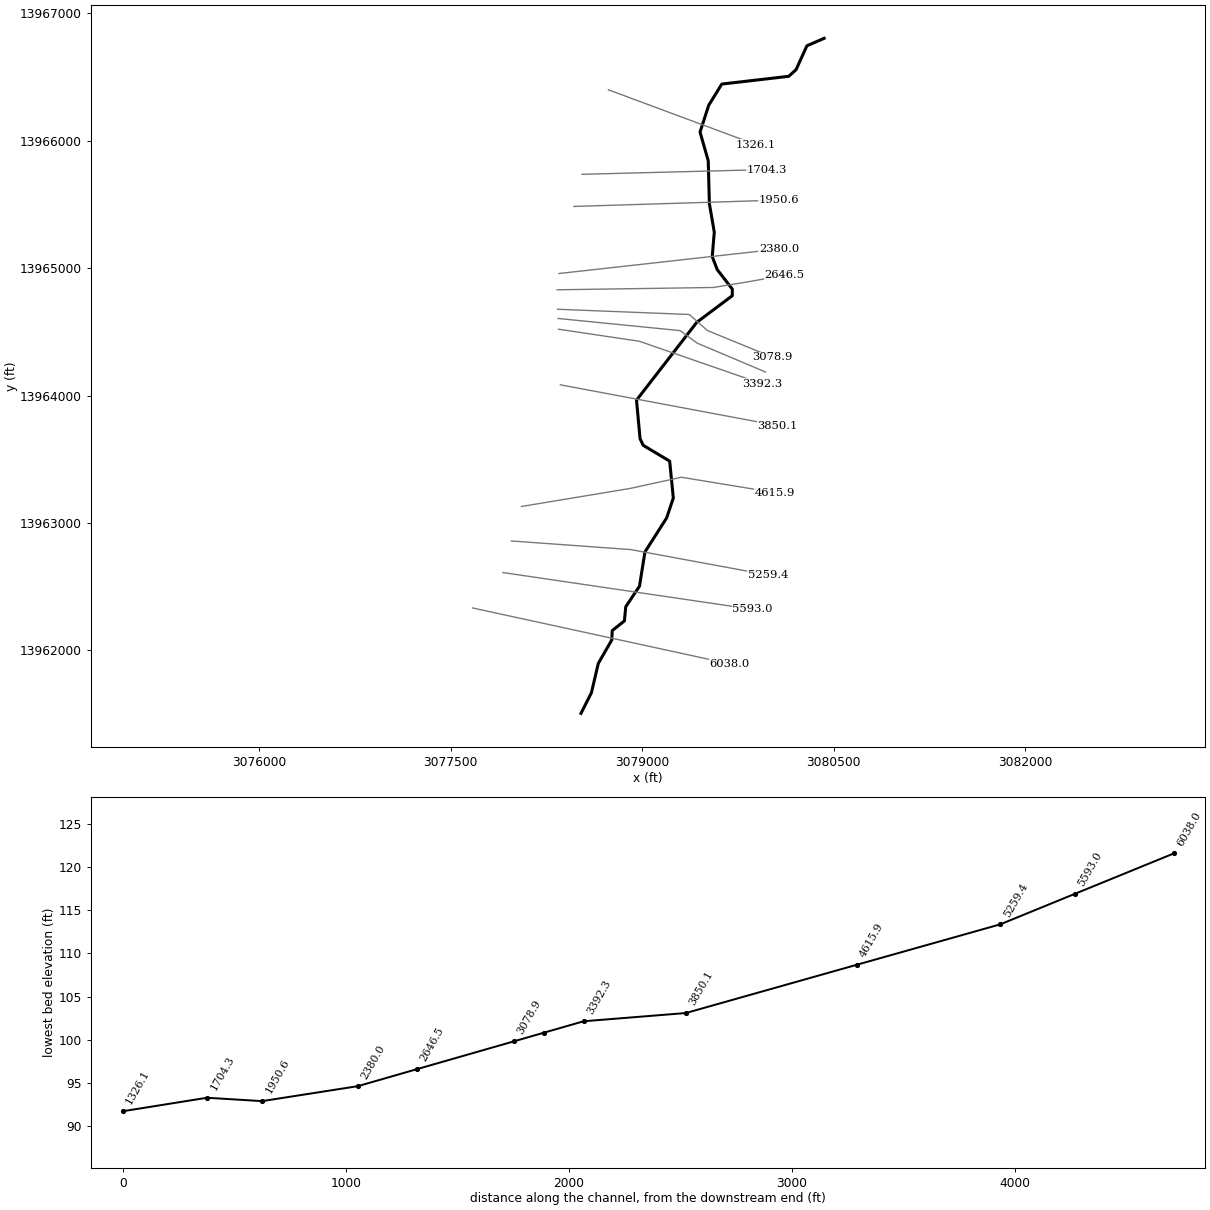
--- J121-00-00.PRJ (project) ---

Proj Title=J121-00-00
Current Plan=p03
Default Exp/Contr=.3,.1
English Units
Geom File=g01
Flow File=f02
Flow File=f03
Plan File=p02
Plan File=p03
Y Axis Title=Elevation
X Axis Title(PF)=Main Channel Distance
X Axis Title(XS)=Station
BEGIN DESCRIPTION:
Spring Creek
Tributary 21.08 to Spring Creek
HCFCD Unit J121-00-00
Flood Hazard Model
10, 2, 1, 0.2% Event
Filename J121-00-00.prj
Prepared by: Halff Associates, Inc.  Date: 03/24/2004
Reviewed by:                  Date:
STATUS Final RAS
END DESCRIPTION:
DSS File=dss
DSS Export Rating Curves= 0
DSS Export Rating Curve Sorted= 0
DSS Export Volume Flow Curves= 0
DXF OffsetX= 0
DXF OffsetY= 0
DXF ScaleX= 1
DXF ScaleY= 10

--- J121-00-00.p03 (plan) ---

Plan Title=Floodway
Version=Version 3.0.1  Mar 2001
Short Identifier=Floodway0607
Geom File=g01
Flow File=f03
Subcritical Flow
K Sum by GR= 0
Std Step Tol= 0.01
Critical Tol= 0.01
Num of Std Step Trials= 20
Max Error Tol= 0.3
Flow Tol Ratio= 0.001
Split Flow NTrial= 30
Split Flow Tol= 0.02
Split Flow Ratio= 0.02
Log Output Level= 0
Friction Slope Method= 1
Unsteady Friction Slope Method= 2
Parabolic Critical Depth
Global Vel Dist= 0 , 0 , 0
Global Log Level= 0
CheckData=True
Encroach Param=-1 ,0,0, 2
Encroach River=J121-00-00
Encroach Reach=Reach - 1
Encroach Node=6038.0
       1  4967.9  5023.9
Encroach Node=5593.0
       1  4967.9  5023.9
Encroach Node=5259.4
       1    4988  5009.9
Encroach Node=4615.9
       1  4981.5  5090.2
Encroach Node=3850.1
       1  4981.5    5050
Encroach Node=3392.3
       1    4986    5050
Encroach Node=3215.7
       1    4986    5050
Encroach Node=3078.9
       1    4986 5052.59
Encroach Node=2646.5
       1    4920  5012.6
Encroach Node=2380.0
       1    4820  5012.6
Encroach Node=1950.6
       1    4600  5030.7
Encroach Node=1704.3
       1    4650  5011.9
Encroach Node=1326.1
       1    4900  5014.3
Encroach Reach=J121-00-00_0133
Encroach Node=6038.0
       1  4967.9  5023.9
Encroach Node=5593.0
       1  4967.9  5023.9
Encroach Node=5259.4
       1    4988  5009.9
Encroach Node=4615.9
       1  4981.5  5090.2
Encroach Node=3850.1
       1  4981.5    5050
Encroach Node=3392.3
       1    4986    5050
Encroach Node=3215.7
       1    4986    5050
Encroach Node=3078.9
       1    4986 5052.59
Encroach Node=2646.5
       1    4920  5012.6
Encroach Node=2380.0
       1    4820  5012.6
Encroach Node=1950.6
       1    4600  5030.7
Encroach Node=1704.3
       1    4650  5011.9
Encroach Node=1326.1
       1    4900  5014.3
Computation Interval=1HOUR
Output Interval=1HOUR
Run HTab= 0
Run UNet= 0
Run PostProcess= 0
UNET Theta= 1
UNET ZTol= 0.02
UNET ZSATol= 0.1
UNET MxIter= 20
UNET MaxInSteps= 20
UNET DtIC= 0
UNET DtMin= 0
UNET MaxCRTS= 20
UNET WFStab= 2
UNET SFStab= 1
UNET WFX= 1
UNET SFX= 1
UNET Convert EG Bridges=-1
UNET Use Existing IB Tables=-1
Instantaneous Interval=1HOUR
DSS File=dss
Write IC File= 0
Write Velocity= 0
Write Detailed= 0

--- J121-00-00.p02 (plan) ---

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Plan Title=FEMA Effective June 2007
Short Identifier=FEMAeff0607
Geom File=g01
Flow File=f02
Encroach Param=-1 ,0,0, 0

--- J121-00-00.f03 (steady flow) ---

Flow Title=Floodway
Version=Version 3.0.1  Mar 2001
Number of Profiles= 2
Profile Names=1PCT_100yr, 1PCTFloodway_100yrFW
River Rch & RM=J121-00-00,J121-00-00_0133,6038.0
    1500    1500
River Rch & RM=J121-00-00,J121-00-00_0133,5259.4
    1550    1550
River Rch & RM=J121-00-00,J121-00-00_0133,4615.9
    1610    1610
River Rch & RM=J121-00-00,J121-00-00_0133,3850.1
    1640    1640
River Rch & RM=J121-00-00,J121-00-00_0133,3392.3
    1700    1700
River Rch & RM=J121-00-00,J121-00-00_0133,2646.5
    1720    1720
River Rch & RM=J121-00-00,J121-00-00_0133,2380.0
    1740    1740
River Rch & RM=J121-00-00,J121-00-00_0133,1950.6
    1760    1760
River Rch & RM=J121-00-00,J121-00-00_0133,1704.3
    1875    1875
Boundary for River Rch & Prof#=J121-00-00,J121-00-00_0133, 1
Up Type= 0
Dn Type= 3
Dn Slope=.005
Boundary for River Rch & Prof#=J121-00-00,J121-00-00_0133, 2
Up Type= 0
Dn Type= 1
Dn Known WS=102.2
DSS Import GetInterval= 0
DSS Import GetPeak= 0
DSS Import FillOption= 0

--- J121-00-00.f02 (steady flow) ---

Flow Title=FEMA Effective June 2007
Version=Version 3.0.1  Mar 2001
Number of Profiles= 4
Profile Names=10PCT_10yr, 2PCT_50yr, 1PCT_100yr, 0.2PCT_500yr
River Rch & RM=J121-00-00,J121-00-00_0133,6038.0
     740    1160    1500    1890
River Rch & RM=J121-00-00,J121-00-00_0133,5259.4
     770    1220    1550    1980
River Rch & RM=J121-00-00,J121-00-00_0133,4615.9
     800    1290    1610    2080
River Rch & RM=J121-00-00,J121-00-00_0133,3850.1
     820    1330    1640    2140
River Rch & RM=J121-00-00,J121-00-00_0133,3392.3
     850    1400    1700    2250
River Rch & RM=J121-00-00,J121-00-00_0133,2646.5
     870    1420    1720    2290
River Rch & RM=J121-00-00,J121-00-00_0133,2380.0
     900    1450    1740    2350
River Rch & RM=J121-00-00,J121-00-00_0133,1950.6
     920    1470    1760    2390
River Rch & RM=J121-00-00,J121-00-00_0133,1704.3
    1050    1613    1875    2672
Boundary for River Rch & Prof#=J121-00-00,J121-00-00_0133, 1
Up Type= 0
Dn Type= 3
Dn Slope=.005
Boundary for River Rch & Prof#=J121-00-00,J121-00-00_0133, 2
Up Type= 0
Dn Type= 3
Dn Slope=.005
Boundary for River Rch & Prof#=J121-00-00,J121-00-00_0133, 3
Up Type= 0
Dn Type= 3
Dn Slope=.005
Boundary for River Rch & Prof#=J121-00-00,J121-00-00_0133, 4
Up Type= 0
Dn Type= 3
Dn Slope=.005
DSS Import GetInterval= 0
DSS Import GetPeak= 0
DSS Import FillOption= 0

--- J121-00-00.g01 (geometry) ---

Geom Title=J121-00-00 June 2007
Version=Version 3.0.1  Mar 2001

River Reach=J121-00-00      ,J121-00-00_0133
Reach XY= 30
      3078521.31   13961506.2208    3078602.9108   13961667.6791
    3078657.0782   13961898.1352    3078762.3436   13962082.1142
    3078766.1052   13962155.5263    3078861.5913   13962231.9152
     3078872.008   13962343.0263    3078979.6469   13962504.4847
    3079022.1816   13962772.7138    3079192.3205    13963040.075
    3079244.4038    13963196.325     3079215.758   13963485.3875
    3079008.2927   13963609.5194    3078983.9872   13963661.6027
    3078956.2094   13963963.6861    3079428.4316   13964574.7972
    3079706.2094   13964783.1305    3079706.2094   13964835.2138
    3079588.1538   13964987.9916    3079549.0203   13965089.7303
    3079565.0323       13965282.    3079526.7367    13965505.364
    3079517.8736   13965841.2902    3079453.6375   13966066.9847
    3079521.3458   13966277.0541    3079623.7764   13966443.7208
    3080148.0819   13966504.4847    3080205.3736    13966556.568
    3080290.4431    13966744.068    3080425.0318   13966802.5092

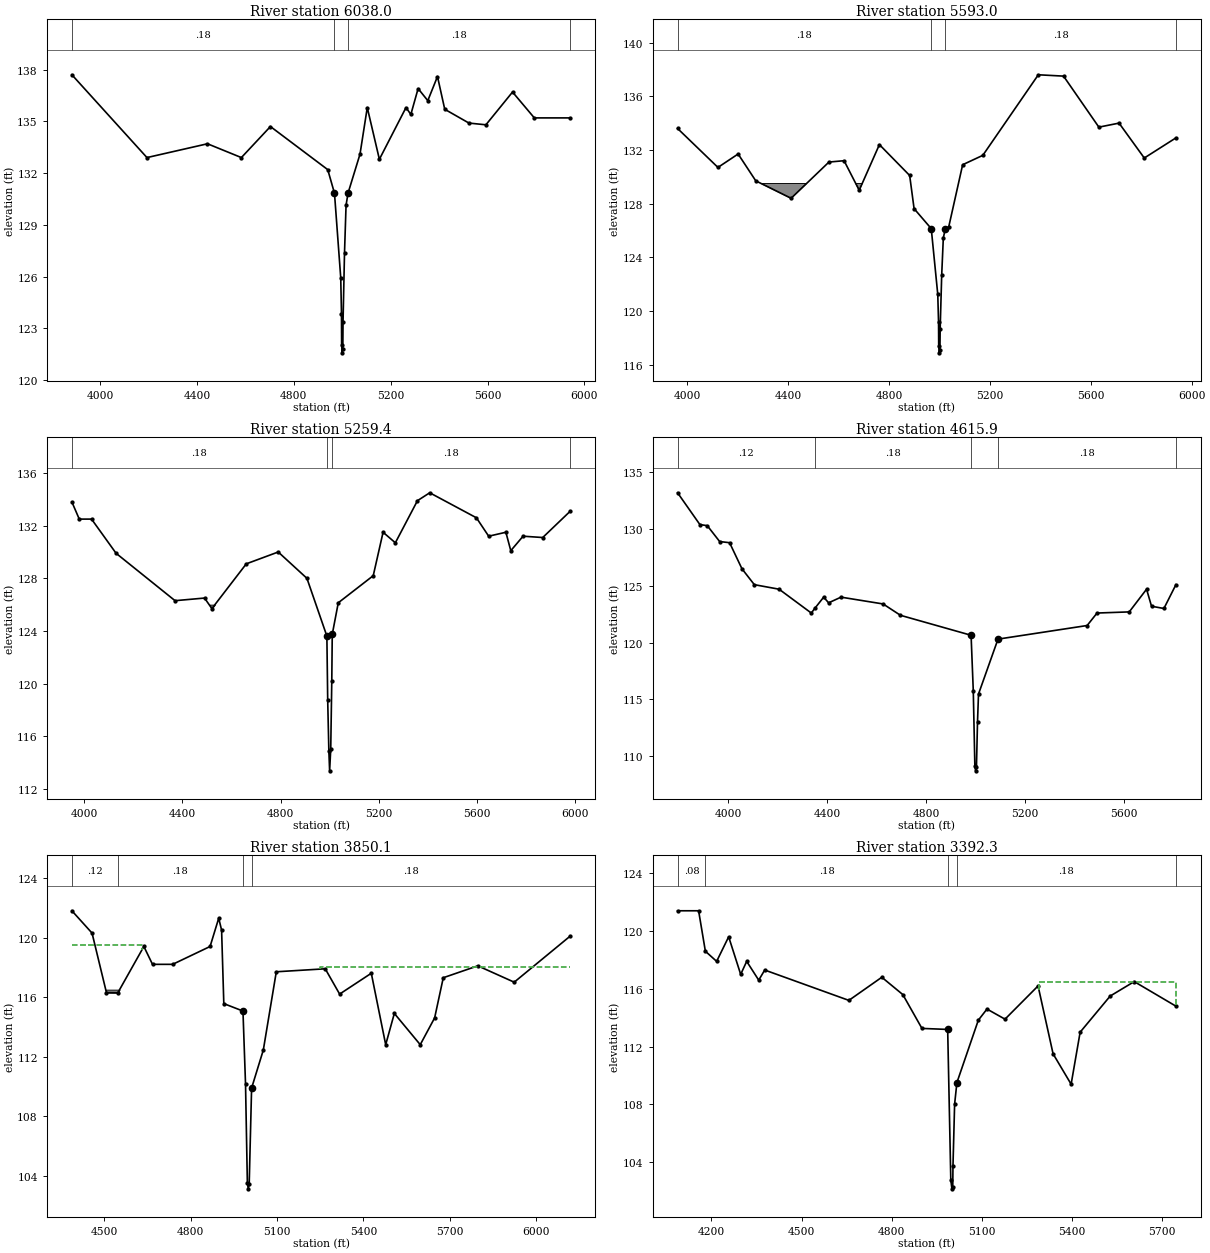
Type RM Length L Ch R = 1 ,6038.0  ,367.7,445,412.16
BEGIN DESCRIPTION:
Cross Section XS11
END DESCRIPTION:
XS GIS Cut Line= 2
    3077671.7881   13962333.5447    3079683.0038   13961895.7049
#Sta/Elev= 30
  3883.3   137.7  4193.3   132.9  4443.3   133.7  4583.3   132.9  4703.3   134.7
  4940.1   132.2  4967.9  130.83  4993.7  125.93  4996.8  123.85  4997.4  122.06
  4999.8  121.58  5002.3  121.78  5003.2  123.37  5009.3  127.38  5015.7  130.14
  5023.9  130.84  5073.3   133.1  5103.3   135.8  5153.3   132.8  5263.3   135.8
  5283.3   135.4  5313.3   136.9  5353.3   136.2  5393.3   137.6  5423.3   135.7
  5523.3   134.9  5593.3   134.8  5703.3   136.7  5793.3   135.2  5941.6   135.2
#Mann= 4 ,-1 , 0
  3883.3     .18       0  4967.9     .06       0  5023.9     .18       0
  5941.6      .2       0
#XS Ineff= 2 , 0
       0    4700     134    5140       0   133.5
Permanent Ineff=
       F       F
Bank Sta=4967.9,5023.9
XS Rating Curve= 0
Exp/Cntr=.3,.1

Type RM Length L Ch R = 1 ,5593.0  ,330.05,333.6,327.47
BEGIN DESCRIPTION:
Cross Section XS10
END DESCRIPTION:
XS GIS Cut Line= 2
    3077910.2863   13962611.1993    3079864.5472   13962322.8657
#Sta/Elev= 30
  3962.3   133.6  4122.3   130.7  4202.3   131.7  4272.3   129.7  4412.3   128.4
  4562.3   131.1  4622.3   131.2  4682.3     129  4762.3   132.4  4882.3   130.1
  4899.8  127.63  4967.9  126.14  4993.7  121.24  4996.8  119.16  4997.4  117.37
  4999.8  116.89  5002.3  117.09  5003.2  118.68  5009.3  122.69  5015.7  125.45
  5023.9  126.15  5036.9  126.25  5092.3   130.9  5172.3   131.6  5392.3   137.6
  5492.3   137.5  5632.3   133.7  5712.3     134  5812.3   131.4  5937.7   132.9
#Mann= 4 ,-1 , 0
  3962.3     .18       0  4967.9     .06       0  5023.9     .18       0
  5937.7      .2       0
#Block Obstruct= 2 , 0
       0    4760   129.5               0
Bank Sta=4967.9,5023.9
XS Rating Curve= 0
Exp/Cntr=.3,.1

Type RM Length L Ch R = 1 ,5259.4  ,622.59,643.5,655.09
BEGIN DESCRIPTION:
Cross Section XS09
END DESCRIPTION:
XS GIS Cut Line= 3
    3077975.6939   13962859.0004    3078910.1913   13962791.3985
    3079983.8692   13962592.5692
#Sta/Elev= 30
  3949.9   133.8  3979.9   132.5  4029.9   132.5  4129.9   129.9  4369.9   126.3
  4489.9   126.5  4519.9   125.7  4659.9   129.1  4789.9     130  4906.8     128
    4988  123.61  4991.4  118.72  4996.1  114.86  4999.2  113.37  5003.7  115.01
    5008  120.21  5009.9  123.74  5034.4  126.14  5176.8   128.2  5216.8   131.5
  5266.8   130.7  5356.8   133.9  5406.8   134.5  5596.8   132.6  5646.8   131.2
  5716.8   131.5  5736.8   130.1  5786.8   131.2  5866.8   131.1  5978.8   133.1
#Mann= 4 ,-1 , 0
  3949.9     .18       0    4988     .06       0  5009.9     .18       0
  5978.8      .2       0
#Block Obstruct= 2 , 0
       0    4650     126               0
Bank Sta=4988,5009.9
XS Rating Curve= 0
Exp/Cntr=.3,.1

Type RM Length L Ch R = 1 ,4615.9  ,809.39,765.8,603.82
BEGIN DESCRIPTION:
Cross Section XS08
END DESCRIPTION:
XS GIS Cut Line= 4
    3078055.2256   13963129.4082    3078903.6505   13963270.4797
    3079308.0862   13963358.7541     3080036.787   13963238.9423
#Sta/Elev= 30
  3796.2   133.2  3886.2   130.4  3916.2   130.3  3966.2   128.9  4006.2   128.8
  4056.2   126.5  4106.2   125.1  4206.2   124.7  4336.2   122.6  4350.7  123.02
  4386.2     124  4406.2   123.5  4456.2     124  4626.2   123.4  4696.3   122.4
  4981.5  120.64  4990.4  115.74  4996.8  109.08    5000  108.69  5003.2  109.04
  5007.5  113.03  5011.5  115.46  5090.2   120.3  5450.2   121.5  5490.2   122.6
  5620.2   122.7  5690.2   124.7  5710.2   123.2  5760.2     123  5808.7   125.1
#Mann= 5 ,-1 , 0
  3796.2     .12       0  4350.7     .18       0  4981.5     .06       0
  5090.2     .18       0  5808.7      .2       0
Bank Sta=4981.5,5090.2
XS Rating Curve= 0
Exp/Cntr=.3,.1

Type RM Length L Ch R = 1 ,3850.1  ,491.93,457.8,406.54
BEGIN DESCRIPTION:
Cross Section XS07
END DESCRIPTION:
XS GIS Cut Line= 2
    3078360.0856   13964084.0812    3080061.2163    13963764.202
#Sta/Elev= 30
  4387.3   121.8  4457.3   120.3  4507.3   116.3  4546.9  116.29  4637.3   119.4
  4667.3   118.2  4737.3   118.2  4867.3   119.4  4897.3   121.3  4907.3   120.5
    4915  115.56  4981.5  115.06  4990.4  110.16  4996.8   103.5    5000  103.11
  5003.2  103.46  5011.5  109.88  5052.2  112.44  5097.3   117.7  5267.3   117.9
  5317.3   116.2  5427.3   117.6  5477.3   112.8  5507.3   114.9  5597.3   112.8
  5647.3   114.6  5677.3   117.3  5797.3   118.1  5923.7     117  6118.3   120.1
#Mann= 4 ,-1 , 0
  4387.3     .12       0  4546.9     .18       0  4981.5     .06       0
  5011.5     .18       0
#XS Ineff= 2 , 0
       0    4630   119.5    5250       0     118
Permanent Ineff=
       F       F
#Block Obstruct= 2 , 0
       0    4575   116.5               0
Bank Sta=4981.5,5011.5
XS Rating Curve= 0
Exp/Cntr=.3,.1

Type RM Length L Ch R = 1 ,3392.3  ,177.3,176.6,174.9
BEGIN DESCRIPTION:
Cross Section XS06
END DESCRIPTION:
XS GIS Cut Line= 3
    3078345.2102    13964520.309    3078977.8404    13964425.888
    3079940.1268   13964091.7417
#Sta/Elev= 30
  4087.2   121.4  4157.2   121.4  4179.7   118.6  4217.2   117.9  4257.2   119.6
  4297.2     117  4317.2   117.9  4357.2   116.6  4377.2   117.3  4657.2   115.2
  4766.8   116.8  4836.8   115.6  4900.4  113.26    4986  113.19  4996.4  102.78
  5000.1  102.16  5002.9  102.28  5003.6  103.71  5009.1  108.02  5016.7  109.51
    5088  113.83  5116.8   114.6  5176.8   113.9  5286.8   116.2  5336.8   111.5
  5396.8   109.4  5426.8     113  5526.8   115.5  5606.8   116.5  5745.5   114.8
#Mann= 5 ,-1 , 0
  4087.2     .08       0  4179.7     .18       0    4986     .06       0
  5016.7     .18       0  5745.5      .2       0
#XS Ineff= 2 , 0
       0                    5290       0   116.5
Permanent Ineff=
       F       F
Bank Sta=4986,5016.7
XS Rating Curve= 0
Exp/Cntr=.3,.1

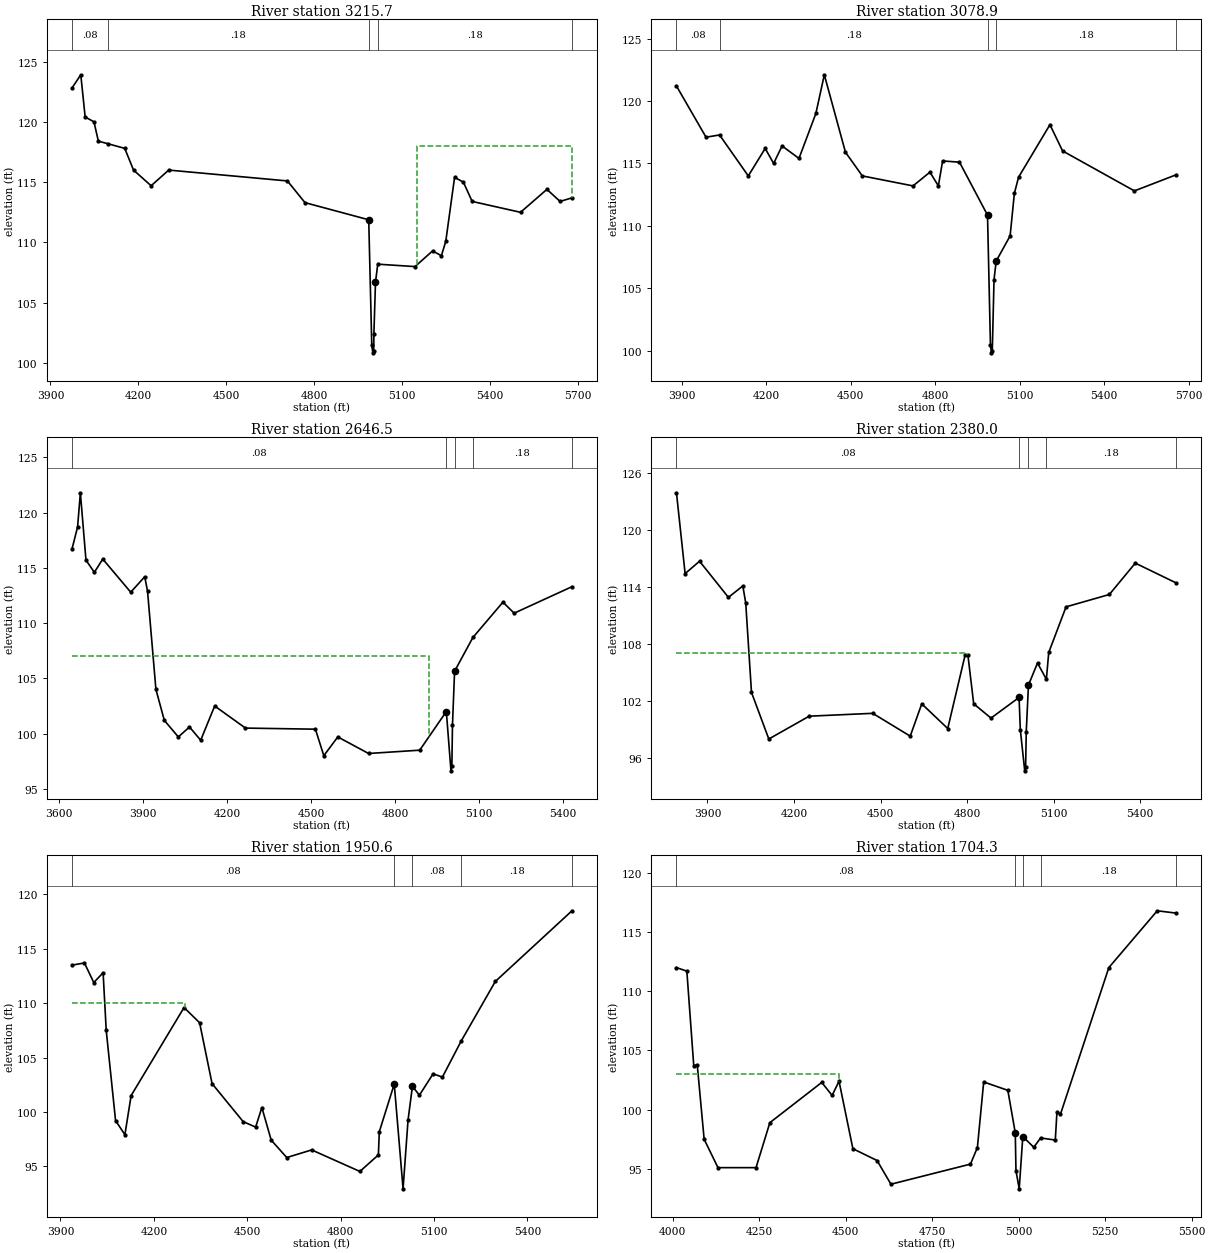
Type RM Length L Ch R = 1 ,3215.7  ,137.6,136.8,125.8
XS GIS Cut Line= 5
    3078341.8189   13964604.5391    3079297.7891   13964509.3184
    3079382.4929   13964447.0362    3079430.2692   13964411.6268
    3079964.7603   13964185.0875
#Sta/Elev= 30
  3973.6   122.8  4003.6   123.9  4018.6   120.4  4048.6     120  4063.6   118.4
  4096.7  118.18  4153.6   117.8  4183.6     116  4243.6   114.7  4303.6     116
  4708.6   115.1  4768.6   113.3    4986  111.88  4996.4  101.47  5000.1  100.85
  5002.9  100.97  5003.6   102.4  5009.1  106.71  5016.8   108.2  5143.9     108
  5203.9   109.3  5233.9   108.9  5248.9   110.1  5278.9   115.4  5308.9     115
  5338.9   113.4  5503.9   112.5  5593.9   114.4  5638.9   113.4  5679.4   113.7
#Mann= 5 ,-1 , 0
  3973.6     .08       0  4096.7     .18       0    4986     .06       0
  5016.8     .18       0  5679.4      .2       0
#XS Ineff= 2 , 0
       0                    5150       0     118
Permanent Ineff=
       F       F
Bank Sta=4986,5009.1
XS Rating Curve= 0
Exp/Cntr=.3,.1

Type RM Length L Ch R = 1 ,3078.9  ,403.6,432.4,457.8
BEGIN DESCRIPTION:
Cross Section XS05.5
END DESCRIPTION:
XS GIS Cut Line= 5
    3078337.7016   13964676.8727    3079368.4386    13964635.837
    3079404.9369   13964604.2732    3079510.5125   13964510.4282
    3080023.2982   13964299.8602
#Sta/Elev= 30
  3881.5   121.2  3986.5   117.1  4034.5  117.28  4136.5     114  4196.5   116.2
  4226.5     115  4256.5   116.4  4316.5   115.4  4376.5     119  4406.5   122.1
  4481.5   115.9  4541.5     114  4721.5   113.2  4781.5   114.3  4811.5   113.2
  4826.5   115.2  4886.5   115.1    4986  110.86  4996.4  100.45  5000.1   99.83
  5002.9   99.95  5009.1  105.69  5016.8  107.18  5066.3   109.2  5081.3   112.6
  5096.3   113.9  5207.6   118.1  5252.6     116  5507.6   112.8  5656.9   114.1
#Mann= 5 ,-1 , 0
  3881.5     .08       0  4034.5     .18       0    4986     .06       0
  5016.8     .18       0  5656.9      .2       0
Bank Sta=4986,5016.8
XS Rating Curve= 0
Exp/Cntr=.3,.1

Type RM Length L Ch R = 1 ,2646.5  ,240.34,266.5,245.49
BEGIN DESCRIPTION:
Cross Section XS05
END DESCRIPTION:
XS GIS Cut Line= 4
    3078334.8131   13964829.6178    3079557.4969   13964847.7746
    3079831.2385   13964892.4064    3080113.3604   13964943.3438
#Sta/Elev= 30
  3645.2   116.7  3665.2   118.7  3675.2   121.8  3695.2   115.7  3725.2   114.6
  3755.2   115.8  3855.2   112.8  3905.2   114.2  3915.2   112.9  3945.2     104
  3975.2   101.2  4025.2    99.7  4065.2   100.6  4105.2    99.4  4155.2   102.5
  4265.2   100.5  4515.2   100.4  4545.2      98  4595.2    99.7  4705.2    98.2
    4888    98.5  4983.1     102  4999.7   96.63  5002.9   97.08    5005  100.76
  5012.6  105.65    5078   108.7  5185.4   111.9  5225.4   110.9  5432.1   113.3
#Mann= 5 ,-1 , 0
  3645.2     .08       0  4983.1     .06       0  5012.6     .08       0
    5078     .18       0  5432.1      .2       0
#XS Ineff= 2 , 0
       0    4920     107               0
Permanent Ineff=
       F       F
Bank Sta=4983.1,5012.6
XS Rating Curve= 0
Exp/Cntr=.3,.1

Type RM Length L Ch R = 1 ,2380.0  ,452.04,429.4,418.98
BEGIN DESCRIPTION:
Cross Section XS04
END DESCRIPTION:
XS GIS Cut Line= 2
    3078349.4739   13964957.3391    3080071.3541   13965149.5132
#Sta/Elev= 30
  3792.9   123.9  3822.9   115.4  3872.9   116.7  3972.9   112.9  4022.9   114.1
  4032.9   112.3  4052.9   102.9  4112.9      98  4252.9   100.4  4472.9   100.7
  4602.9    98.3  4642.9   101.7  4732.9    99.1  4792.9   106.8  4802.9   106.8
  4822.9   101.7  4882.9   100.2  4980.1  102.37  4984.5   98.95  4999.7   94.65
  5002.9    95.1    5005   98.78  5012.6  103.67    5044  105.99  5074.7  104.28
  5082.9   107.1  5142.9   111.9  5292.9   113.2  5382.9   116.5  5525.5   114.4
#Mann= 5 ,-1 , 0
  3792.9     .08       0  4980.1     .06       0  5012.6     .08       0
  5074.7     .18       0  5525.5      .2       0
#XS Ineff= 2 , 0
       0    4800     107               0
Permanent Ineff=
       F       F
Bank Sta=4980.1,5012.6
XS Rating Curve= 0
Exp/Cntr=.3,.1

Type RM Length L Ch R = 1 ,1950.6  ,247.7,246.3,245.15
BEGIN DESCRIPTION:
Cross Section XS03
END DESCRIPTION:
XS GIS Cut Line= 2
    3078465.5645   13965483.4552    3080070.9774   13965533.2906
#Sta/Elev= 30
    3937   113.5    3977   113.7    4007   111.9    4037   112.8    4047   107.5
    4077    99.2    4107    97.9    4127   101.5    4297   109.6    4347   108.2
    4387   102.6    4487    99.1    4527    98.6    4547   100.4    4577    97.4
    4627    95.8    4707    96.5  4861.9   94.52  4921.3   96.04  4924.3   98.18
  4972.3  102.56  5000.6   92.92  5016.6   99.25  5030.7  102.36    5053  101.53
    5097   103.5    5127   103.2    5187   106.5    5297     112  5543.2   118.5
#Mann= 5 ,-1 , 0
    3937     .08       0  4972.3     .06       0  5030.7     .08       0
    5187     .18       0  5543.2      .2       0
#XS Ineff= 2 , 0
       0    4300     110               0
Permanent Ineff=
       F       F
Bank Sta=4972.3,5030.7
XS Rating Curve= 0
Exp/Cntr=.3,.1

Type RM Length L Ch R = 1 ,1704.3  ,445.14,378.2,353.88
BEGIN DESCRIPTION:
Cross Section XS02
END DESCRIPTION:
XS GIS Cut Line= 2
    3078529.8075   13965735.7609    3079974.8669   13965772.8137
#Sta/Elev= 30
  4010.6     112  4040.6   111.7  4060.6   103.7  4070.6   103.8  4090.6    97.5
  4130.6    95.1  4240.6    95.1  4280.6    98.9  4430.6   102.3  4460.6   101.2
  4480.6   102.4  4520.6    96.7  4590.6    95.7  4630.6    93.7  4860.6    95.4
  4880.6    96.8  4898.8  102.34  4968.6  101.63  4990.1   98.04  4992.1   94.85
  5001.5   93.31  5011.9   97.73  5043.6   96.82  5063.3   97.61  5105.8   97.43
  5110.6    99.8  5120.6    99.6  5260.6     112  5400.6   116.8  5456.1   116.6
#Mann= 5 ,-1 , 0
  4010.6     .08       0  4990.1     .06       0  5011.9     .08       0
  5063.3     .18       0  5456.1      .2       0
#XS Ineff= 2 , 0
       0    4480     103               0
Permanent Ineff=
       F       F
Bank Sta=4990.1,5011.9
XS Rating Curve= 0
Exp/Cntr=.3,.1

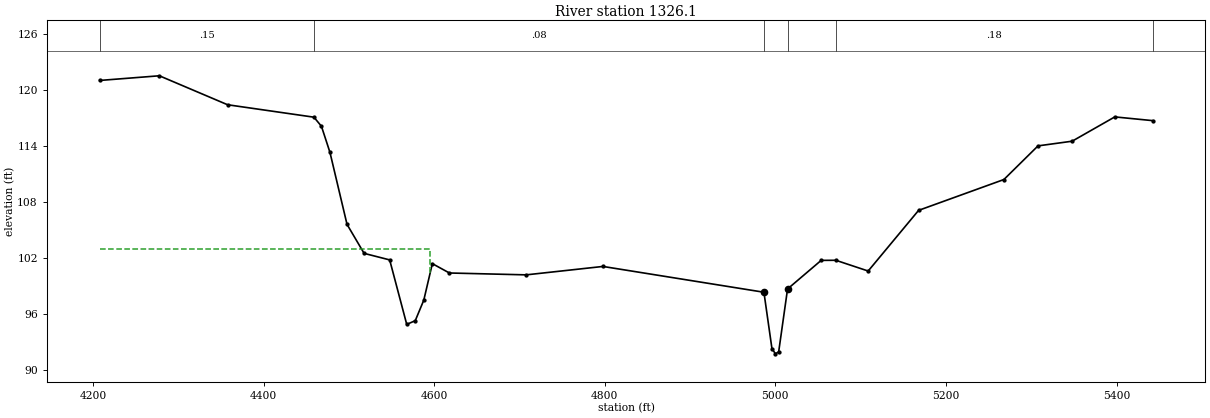
Type RM Length L Ch R = 1 ,1326.1  ,0,0,0
BEGIN DESCRIPTION:
Cross Section XS01
END DESCRIPTION:
XS GIS Cut Line= 2
    3078736.1306   13966398.6922    3079893.0246   13965967.9717
#Sta/Elev= 30
  4207.9     121  4277.9   121.5  4357.9   118.4  4459.1  117.07  4467.9   116.1
  4477.9   113.3  4497.9   105.6  4517.9   102.5  4547.9   101.8  4567.9    94.9
  4577.9    95.3  4587.9    97.5  4597.9   101.4  4617.9   100.4  4707.9   100.2
  4797.9   101.1  4986.6   98.34    4996   92.31  5000.1   91.75  5003.9   91.97
  5014.3   98.69  5053.7  101.75  5070.9  101.76  5108.8  100.61  5167.9   107.1
  5267.9   110.4  5307.9     114  5347.9   114.5  5397.9   117.1  5442.4   116.7
#Mann= 6 ,-1 , 0
  4207.9     .15       0  4459.1     .08       0  4986.6     .06       0
  5014.3     .08       0  5070.9     .18       0  5442.4      .2       0
#XS Ineff= 2 , 0
       0    4595     103               0
Permanent Ineff=
       F       F
Bank Sta=4986.6,5014.3
XS Rating Curve= 0
Exp/Cntr=.3,.1

Chan Stop Cuts=-1